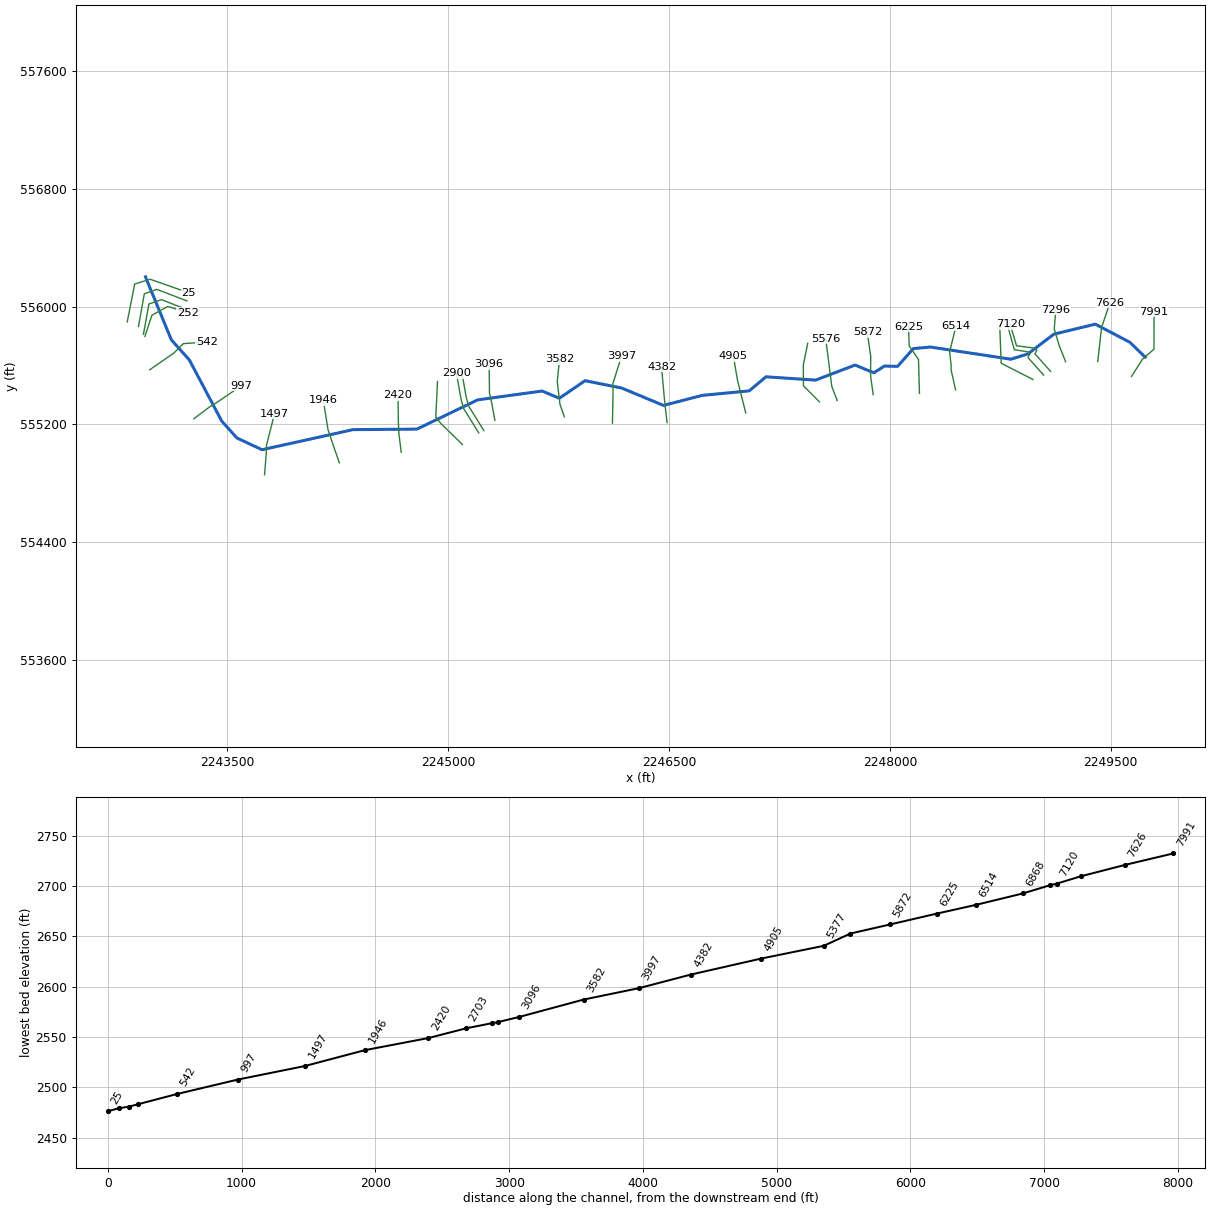
--- LOGANRN.prj (project) ---

Proj Title=LOGANRN
Current Plan=p01
Default Exp/Contr=0,0
English Units
Geom File=g01
Flow File=f01
Plan File=p01
BEGIN DESCRIPTION:
----------MODEL BY WOOD PLC 2022----------
AFH study
Randolph County, WV
HEC-RAS Version: RAS 6.2
Vertical Datum: NAVD88
Projection: NAD 1983 StatePlane West Virginia S FIPS 4702 (US Feet)
Terrain: 1-meter LIDAR (FEMA Region III 3DEP collected 2016-2018)
Land Use: 2019 NLCD
Hydrologic Method:
WV SIR2010-5033 regression equations
Additional Model Notes:
None
END DESCRIPTION:
DSS Export Rating Curves= 0
DSS Export Rating Curve Sorted= 0
DSS Export Volume Flow Curves= 0
DXF OffsetX= 0
DXF OffsetY= 0
DXF ScaleX= 0
DXF ScaleY= 0

--- LOGANRN.p01 (plan) ---

Plan Title=Floodplain
Program Version=6.20
Short Identifier=Floodplain
Geom File=g01
Flow File=f01
Subcritical Flow
K Sum by GR= 0
Std Step Tol= 0.01
Critical Tol= 0.01
Num of Std Step Trials= 20
Max Error Tol= 0.3
Flow Tol Ratio= 0.001
Split Flow NTrial= 30
Split Flow Tol= 0.02
Split Flow Ratio= 0.02
Log Output Level= 0
Friction Slope Method= 1
Unsteady Friction Slope Method= 2
Unsteady Bridges Friction Slope Method= 1
Parabolic Critical Depth
Global Vel Dist= 0 , 0 , 0
Global Log Level= 0
CheckData=True
Encroach Param=-1 ,0,0, 0
Mapping Interval=1HOUR
Computation Time Step Use Courant=        0
Computation Time Step Use Time Series=    0
Computation Time Step Count To Double=0
Computation Time Step Max Doubling=0
Computation Time Step Max Halving=0
Computation Time Step Residence Courant=0
Run HTab= 0
Run UNet= 0
Run Sediment= 0
Run PostProcess= 0
Run WQNet= 0
Run RASMapper=-1
UNET Theta= 0
UNET Theta Warmup= 0
UNET ZTol= 0
UNET ZSATol= 0
UNET MxIter= 0
UNET Max Iter WO Improvement= 0
UNET MaxInSteps= 0
UNET DtIC= 0
UNET DtMin= 0
UNET MaxCRTS= 0
UNET WFStab= 0
UNET SFStab= 0
UNET WFX= 1
UNET SFX= 1
UNET Gravity=32.174
UNET 1D Methodology=Finite Difference
UNET DSS MLevel= 1
UNET Pardiso=0
UNET DZMax Abort= 0
UNET Use Existing IB Tables= 0
UNET Froude Reduction=False
UNET Froude Limit= 0
UNET Froude Power= 0
UNET D1 Cores= 0
UNET WindReference=Eulerian
UNET WindDragFormulation=Hsu (1988)
UNET D2 Coriolis=0
UNET D2 Cores= 0
UNET D2 Theta= 1
UNET D2 Theta Warmup= 1
UNET D2 Z Tol= 0.01
UNET D2 Volume Tol= 0.01
UNET D2 Max Iterations= 20
UNET D2 Equation= 0
UNET D2 RampUpFraction=0.1
UNET D2 TimeSlices= 1
UNET D2 Turbulence Formulation=Non-Conservative (original)
UNET D2 Eddy Viscosity=0.3
UNET D2 Transverse Eddy Viscosity=0.1
UNET D2 Smagorinsky Mixing=0
UNET D2 BCVolumeCheck=0
UNET D2 Cores=0
UNET D2 SolverType=PARDISO (Direct)
UNET D2 Minimum Iterations= 2147483647
UNET D2 Maximum Iterations= 2147483647
UNET D2 Restart Number= 10
UNET D2 Relaxation Coeff=1.3
UNET D2 SOR Precondition Iterations= 10
UNET D2 ILUT Maximum Fill= 8
UNET D2 ILUT Tolerance=1E-08
UNET D1D2 MaxIter= 0
UNET D1D2 ZTol=0.01
UNET D1D2 QTol=0.1
UNET D1D2 MinQTol=1
Write IC File= 0
Write IC File at Fixed DateTime=0
Write IC File at Sim End=0
Echo Input=False
Echo Parameters=False
Echo Output=False
Write Detailed= 0
HDF Write Warmup=0
HDF Write Time Slices=0
HDF Flush=0
HDF Compression= 1
HDF Chunk Size= 1
HDF Spatial Parts= 1
HDF Use Max Rows=0
HDF Fixed Rows= 1
Calibration Method= 0
Calibration Iterations= 20
Calibration Max Change=0.05
Calibration Tolerance=0.2
Calibration Maximum=1.5
Calibration Minimum=0.5
Calibration Optimization Method= 1
WQ AD Non Conservative
WQ ULTIMATE=-1
WQ Max Comp Step=1HOUR
WQ Output Interval=15MIN
WQ Output Selected Increments= 0
WQ Output face flow=0
WQ Output face velocity=0
WQ Output face area=0
WQ Output face dispersion=0
WQ Output cell volume=0
WQ Output cell surface area=0
WQ Output cell continuity=0
WQ Output cumulative cell continuity=0
WQ Output face conc=0
WQ Output face dconc_dx=0
WQ Output face courant=0
WQ Output face peclet=0
WQ Output face adv mass=0
WQ Output face disp mass=0
WQ Output cell mass=0
WQ Output cell source sink temp=0
WQ Output nsm pathways=0
WQ Output nsm derived pathways=0
WQ Create Restart=0
WQ Fixed Restart=0
WQ System Summary=0
WQ Write To DSS=0
Sorting and Armoring Iterations= 10
XS Update Threshold= 0.02
Bed Roughness Predictor= 0
Hydraulics Update Threshold= 0.02
Energy Slope Method= 1
Volume Change Method= 1
Sediment Retention Method= 0
Sediment TS Multiplier= 1
Warm Up Method= 0
XS Weighting Method= 0
Number of US Weighted Cross Sections= 1
Number of DS Weighted Cross Sections= 1
Upstream XS Weight=0
Main XS Weight=1
Downstream XS Weight=0
Number of DS XS's Weighted with US Boundary= 1
Upstream Boundary Weight= 1
Weight of XSs Associated with US Boundary= 0
Number of US XS's Weighted with DS Boundary= 1
Downstream Boundary Weight= 0.5
Weight of XSs Associated with DS Boundary= 0.5
Percentile Method= 0
Sediment Output Level= 3
Mass or Volume Output= 0
Output Increment Type= 1
Profile and TS Output Increment= 1
Transport Output Increment 1
XS Output Flag= 0
XS Output Increment= 10
Read HDF5 Sediment Hotstart= 0
Sediment Hotstart Type= 0
Write Gradation File= 0
Read Gradation Hotstart= 0
Write HDF5 File= 1
Write Binary Output= 1
Write DSS Sediment File= 0
DSS Sediment Output Type= 1
SV Curve= 0
Specific Gage Flag= 0
Subcell Erosion Methods= 0
Subcell Deposition Methods= 0
Advection Scheme= 1
Matrix Solver= 0
Implicit Weighting Factor= 1
Maximum Outer Loop Convergence Iterations= 5
Convergence Maximum Absolute= 0.001
Convergence RMSE= 0.0001
Grain Fractions Max Abs Error= 0.001
Max Subgrid Regions= 1
Max Subgrid Length Scale= 3.402823E+38
Initial Layer Thickness= 3.402823E+38
Min Layer Thickness= 3.402823E+38
Max Layer Thickness= 3.402823E+38
Number of Layers= 5

--- LOGANRN.f01 (steady flow) ---

Flow Title=Flow
Program Version=6.20
Number of Profiles= 1
Profile Names=P100yr
River Rch & RM=LOGANRN,Main,7991
     489
River Rch & RM=LOGANRN,Main,6225
     556
River Rch & RM=LOGANRN,Main,3997
     625
Boundary for River Rch & Prof#=LOGANRN,Main            , 1
Up Type= 0
Dn Type= 3
Dn Slope=0.03674
DSS Import GetInterval= 0
DSS Import GetPeak= 0
DSS Import FillOption= 0

--- LOGANRN.g01 (geometry) ---

Geom Title=Geometry
Program Version=6.20

River Reach=LOGANRN         ,Main
Reach XY= 30
     2249733.452      555656.394     2249629.535      555757.436
     2249395.201      555880.551      2249113.66      555812.644
     2248936.577      555678.095     2248821.242      555642.474
     2248275.119      555725.144     2248159.494      555714.727
     2248052.202      555593.894     2247962.098      555595.977
     2247891.786      555550.144     2247763.661      555602.748
2247495.10688311555500.486978381 2247158.4407242555522.986797995
2247044.47437462555427.460625641     2246725.609      555396.791
     2246462.241      555328.751     2246177.829      555447.065
      2245929.91      555496.5532245755.33446966555377.149992782
2245638.44141786555426.4172535862245200.09208489555366.193214676
     2244788.067      555167.737     2244354.514      555164.209
2243736.30091069555027.7992838962243565.20511307555107.833517816
     2243462.557       555222.52     2243242.738       555637.59
     2243120.391      555774.136     2242944.877      556201.491

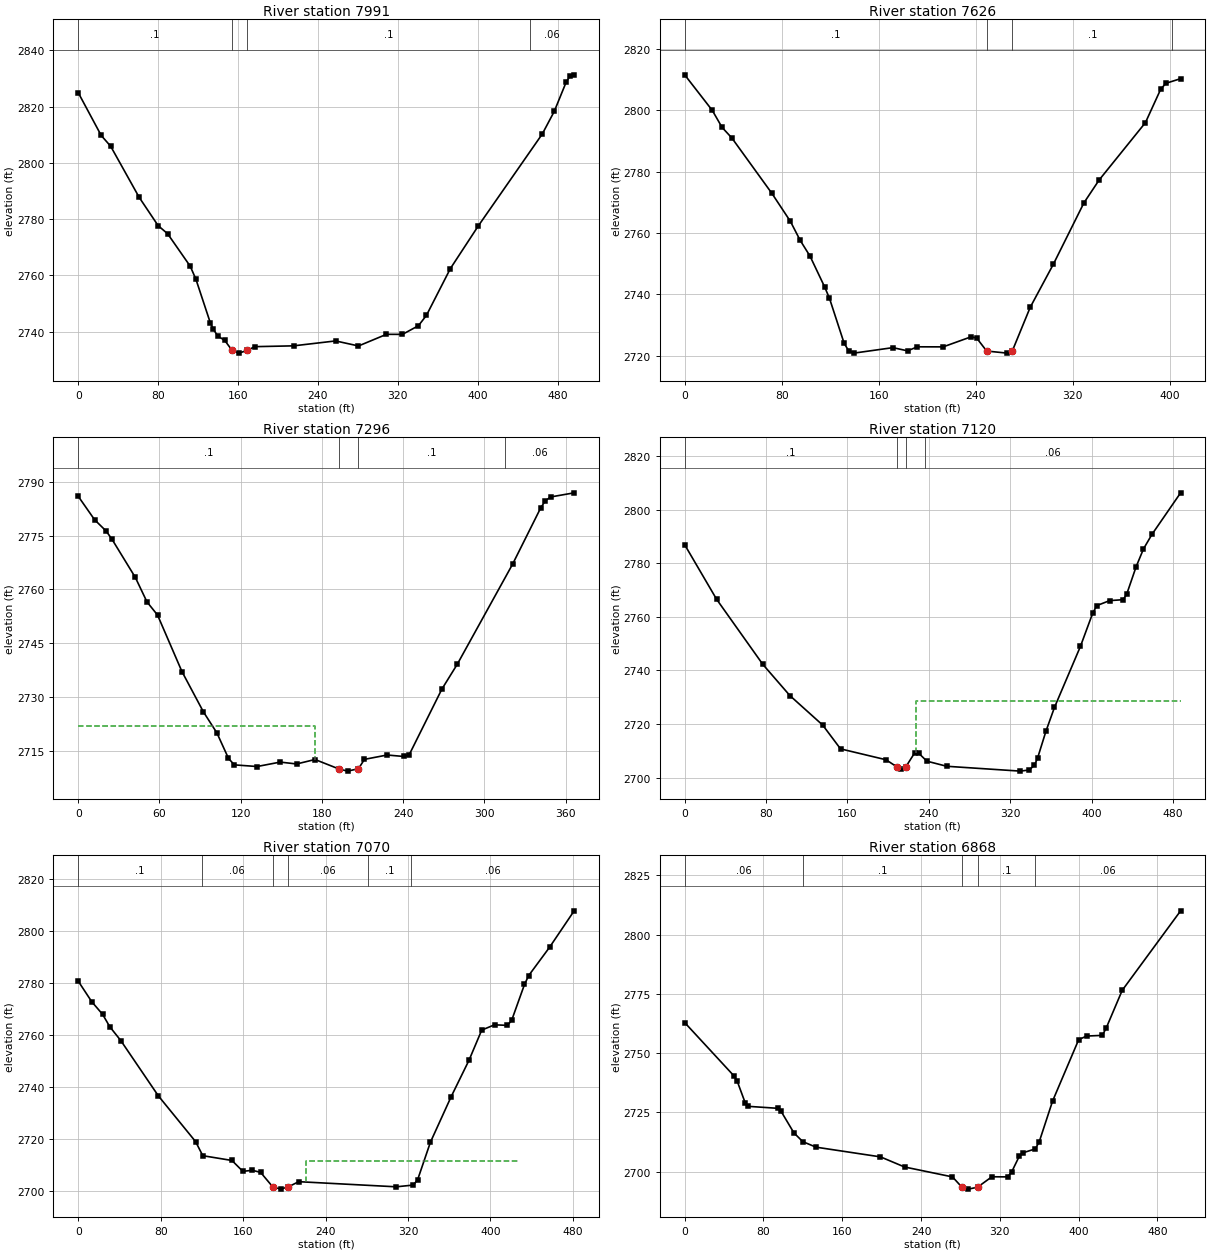
Type RM Length L Ch R = 1 ,7991    ,362.6,365.5,372.1
XS GIS Cut Line= 4
2249640.77321497555525.761125419 2249715.1239127555642.212347539
 2249793.2436343555710.5219512612249793.95482563555965.054294695
#Sta/Elev= 30
       0    2825      23 2809.77    32.5 2805.92      61 2787.77      80 2777.69
    89.5 2774.81   112.1 2763.27   117.8 2758.66   132.2 2743.18   135.3 2740.83
   139.6 2738.48   146.7 2736.84  154.162733.284   160.9 2732.34  168.942733.284
   176.8 2734.64   215.6 2734.93   257.7 2736.68   280.6 2734.89   308.6 2739.03
   324.6 2739.01   340.6 2742.09   348.6 2745.76   372.6 2762.43   400.6 2777.62
   464.6 2810.29   476.6 2818.34   488.6 2828.82   492.6 2831.01   496.5 2831.33
#Mann= 4 ,-1,0
       0      .1       0  154.16    .045       0  168.94      .1       0
  451.94     .06       0
Bank Sta=154.16,168.94
XS Rating Curve= 0 ,0
Exp/Cntr(USF)=0,0
Exp/Cntr=0.3,0.1

Type RM Length L Ch R = 1 ,7626    ,326.3,329.4,338.7
XS GIS Cut Line= 3
2249411.37624922555626.5412456952249437.19802494555857.271306145
2249493.83933941 556024.69636806
#Sta/Elev= 30
       0 2811.58    22.8 2799.96    30.8 2794.45    38.9 2790.98    71.9 2772.92
    87.2 2763.76    95.2 2757.61   103.3 2752.48   115.4  2742.4   119.4 2738.67
   131.5 2723.99   135.5  2721.4   139.5 2720.81   171.7  2722.6   183.8 2721.55
   191.8 2722.87   213.1 2722.85   236.3 2726.15   240.8 2725.69     249 2721.49
   265.9 2720.81  270.11  2721.5   284.9 2735.76   303.9 2749.75   329.2 2769.84
   341.7 2777.27   379.9    2796   392.5 2806.91   396.8 2808.82   408.9 2810.33
#Mann= 4 ,-1,0
       0      .1       0     249    .045       0  270.11      .1       0
  402.17     .06       0
Bank Sta=249,270.11
XS Rating Curve= 0 ,0
Exp/Cntr(USF)=0,0
Exp/Cntr=0.3,0.1

Type RM Length L Ch R = 1 ,7296    ,170.7,175.7,179
XS GIS Cut Line= 4
2249192.89609861555625.9252362512249149.33703524 555736.19798777
2249115.79776501555848.1906426132249126.92674877555978.505636265
#Sta/Elev= 30
       0  2785.9    12.1 2779.38    20.7 2776.21      25 2773.92    42.2 2763.34
    50.8 2756.54    58.6 2752.89    76.6  2737.2    92.5 2725.97   102.4 2720.16
     111 2713.06   115.3 2711.26   132.1  2710.8   149.2 2712.03   161.3 2711.51
   174.9 2712.75   192.3 2710.16   198.9 2709.52     207 2710.19   211.4 2712.79
   228.2    2714   240.5 2713.59   244.5  2714.1   268.6 2732.31     280 2739.24
   320.8 2767.01   341.5  2782.6   344.9 2784.61   348.9 2785.71   366.3 2786.86
#Mann= 4 ,-1,0
       0      .1       0   192.3    .045       0     207      .1       0
  315.47     .06       0
#XS Ineff= 2 , 0
          174.79 2722.18
Permanent Ineff=
       F       F
Bank Sta=192.3,207
XS Rating Curve= 0 ,0
Exp/Cntr=0.3,0.1

Type RM Length L Ch R = 1 ,7120    ,52.7,50.6,48.6
XS GIS Cut Line= 6
2249091.25504927 555559.901286222248984.92115257555679.157004455
2248997.25346794555703.3816455862248986.10820279555717.283421502
2248859.72522203555733.5562633172248817.06765711555880.159223675
#Sta/Elev= 30
       0 2786.94    31.4 2766.55    76.8 2742.25   103.5 2730.56   135.7 2719.56
   153.2 2710.69   197.9 2706.63  208.26 2704.05   212.8 2703.22  217.47 2704.03
   226.3 2709.33     230 2709.08   238.1  2706.1   257.6 2704.19     330 2702.38
   338.6 2702.81   343.8 2704.57   346.9 2707.26   355.2 2717.38   363.5 2726.18
     389 2748.95     401  2761.3   405.1  2764.2   417.7 2766.06   430.9 2766.41
   434.4 2768.36   443.8 2778.75     451 2785.38   459.4 2790.84   487.5 2806.32
#Mann= 4 ,-1,0
       0      .1       0  208.26    .045       0  217.47      .1       0
  236.26     .06       0
#XS Ineff= 2 , 0
                          227.39         2728.46
Permanent Ineff=
       F       F
Bank Sta=208.26,217.47
XS Rating Curve= 0 ,0
Exp/Cntr=0.3,0.1

Type RM Length L Ch R = 1 ,7070    ,206.1,202.1,196.3
XS GIS Cut Line= 6
2249043.97640802555534.3468094452248937.64251132 555653.60252768
2248949.97482669555677.8271688112248938.82956154555691.728944727
2248844.47772168555707.4879562782248797.33288745 555879.68934424
#Sta/Elev= 30
       0 2780.71    13.2 2772.77    23.7 2767.94    30.6 2763.21    41.3 2757.89
    77.8 2736.62   113.9 2719.07   120.9 2713.65   149.2 2711.82   159.8 2707.63
   168.9 2708.05     177 2707.25   188.72701.723   196.6 2700.81   203.92701.693
     214 2703.67   308.6  2701.7   325.2 2702.37   329.4 2704.43   341.8 2718.82
   361.8 2736.21   379.3 2750.36   391.6  2761.9     404 2763.93   416.5 2763.72
   420.6 2765.59   433.1 2779.43   437.2 2782.86   457.4  2793.7   481.3 2807.72
#Mann= 6 ,-1,0
       0      .1       0     120     .06       0   188.7    .045       0
   203.9     .06       0  281.43      .1       0  322.75     .06       0
#XS Ineff= 1 ,-1
  220.68   426.8 2711.45
Permanent Ineff=
       F
Bank Sta=188.7,203.9
XS Rating Curve= 0 ,0
Exp/Cntr=0.3,0.1

Type RM Length L Ch R = 1 ,6868    ,351.9,353.7,353.2
XS GIS Cut Line= 4
2248970.94252107555504.9772973922248755.83633018555614.879798597
2248751.67152764555718.999861977 2248745.7242521555876.634857216
#Sta/Elev= 30
       0 2762.89    49.8 2740.51    53.2 2738.31    61.5 2728.99    64.6 2727.56
    94.4 2726.74    97.4 2725.79   110.9 2716.38   119.9 2712.68   133.4 2710.35
   198.8 2706.26   223.2    2702   271.9 2697.81  281.52 2693.45   287.9 2692.66
   297.3 2693.47   311.9 2697.87   327.9 2697.82   331.9 2699.85   339.9  2706.7
   343.9 2708.04   355.9 2709.62   359.9 2712.55   373.5 2729.78     400 2755.67
     408  2757.2     424 2757.49     428 2760.62   444.2 2776.48   503.5    2810
#Mann= 5 ,-1,0
       0     .06       0     120      .1       0  281.52    .045       0
   297.3      .1       0  355.76     .06       0
Bank Sta=281.52,297.3
XS Rating Curve= 0 ,0
Exp/Cntr(USF)=0,0
Exp/Cntr=0.3,0.1

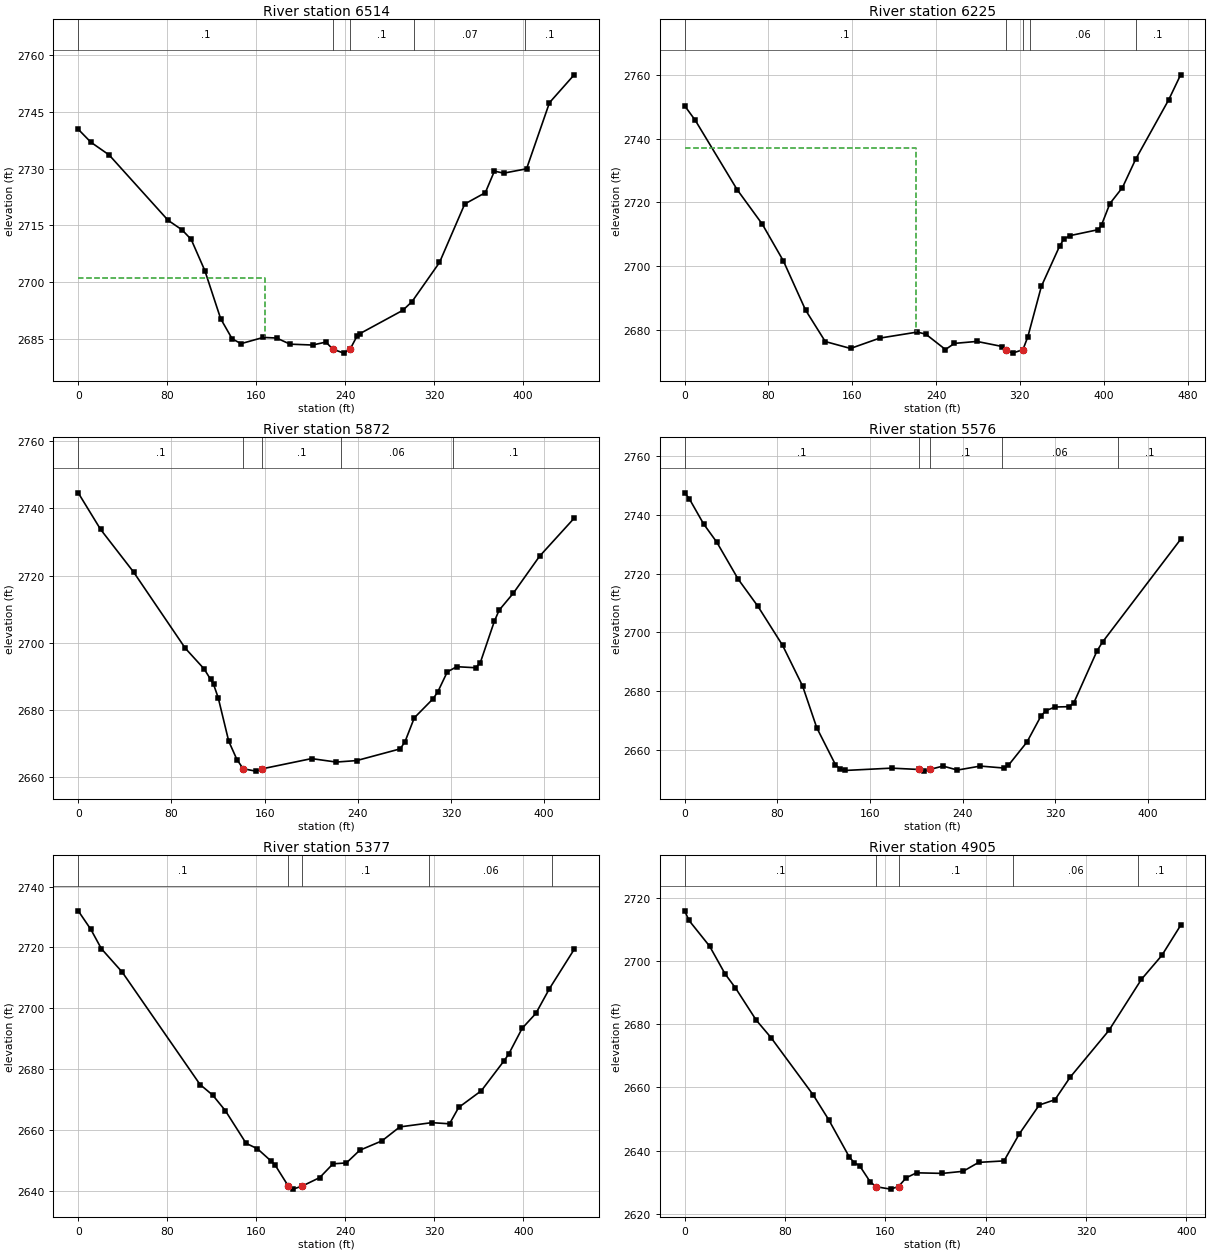
Type RM Length L Ch R = 1 ,6514    ,284.5,289.3,293.4
XS GIS Cut Line= 5
2248446.04028123555434.0615296272248415.94446412555568.869713209
2248415.21047044555608.7882628782248405.39702772555691.979883262
2248449.86368709555870.754473477
#Sta/Elev= 30
       0 2740.37    11.4 2736.94    27.8 2733.58    80.8 2716.32    93.4 2713.78
   101.6 2711.26   113.9    2703   128.1 2690.32   138.4 2685.01   146.4 2683.72
   166.4 2685.37   178.4 2685.21   190.5 2683.59   210.7 2683.36   222.8 2684.14
  228.892682.282   238.8 2681.22  244.562682.284   250.9 2685.81   253.2 2686.35
   291.9 2692.53   300.2 2694.83   324.9 2705.17   347.6 2720.62   366.1 2723.61
   374.3 2729.31   382.6 2728.77   403.2 2729.92   423.8 2747.39     446 2754.75
#Mann= 5 ,-1,0
       0      .1       0  228.89    .045       0  244.56      .1       0
  301.82     .07       0  401.82      .1       0
#XS Ineff= 2 , 0
          167.87 2700.97
Permanent Ineff=
       F       F
Bank Sta=228.89,244.56
XS Rating Curve= 0 ,0
Exp/Cntr=0.3,0.1

Type RM Length L Ch R = 1 ,6225    ,355.7,352.4,345.5
XS GIS Cut Line= 4
2248200.64974311555411.0607576132248194.29404931555640.773690727
2248131.27325039555731.8199850272248126.05716079555864.568108822
#Sta/Elev= 30
       0 2750.37    10.1 2745.82    50.1 2724.01    74.1 2713.16    94.2 2701.62
   115.4 2686.16   134.2 2676.27   158.3  2674.1   186.2 2677.35   222.2 2679.26
   230.3 2678.56   248.9 2673.77   257.5 2675.69   278.9 2676.31   303.3  2674.7
  306.34 2673.72     313 2672.63  322.862673.718   327.6 2677.81   340.5 2693.64
   357.9 2706.28   361.9 2708.45   367.9 2709.57   394.9 2711.45   397.9 2712.92
   405.9 2719.65   417.9 2724.69   430.4 2733.52     462 2752.25   473.4 2760.11
#Mann= 5 ,-1,0
       0      .1       0  306.34    .045       0  322.86      .1       0
   329.8     .06       0  430.53      .1       0
#XS Ineff= 2 , 0
          220.94 2737.17
Permanent Ineff=
       F       F
Bank Sta=306.34,322.86
XS Rating Curve= 0 ,0
Exp/Cntr(USF)=0,0
Exp/Cntr=0.3,0.1

Type RM Length L Ch R = 1 ,5872    ,295.4,296.2,296.3
XS GIS Cut Line= 4
2247886.64764391555402.1354508792247869.12092941555526.308475403
2247869.54291439555662.3838691272247846.37122573555824.917011308
#Sta/Elev= 30
       0 2744.65    19.2 2733.76    47.5 2721.07    91.9 2698.37   108.1  2692.2
   113.6 2689.11   116.2  2687.6   120.2 2683.58   129.2 2670.67   136.3 2665.17
   141.62662.487   152.3 2661.77   158.1 2662.47   200.3  2665.5   221.5 2664.47
     239 2664.91   276.4  2668.4   280.5 2670.53   288.5 2677.65   304.7 2683.35
   308.7 2685.41   316.8 2691.32   324.9 2692.87   341.1 2692.56   345.1 2694.03
   357.2 2706.39   361.3  2709.7   373.4 2714.72     396 2725.76   425.7 2737.09
#Mann= 5 ,-1,0
       0      .1       0   141.6    .045       0   158.1      .1       0
   225.4     .06       0  321.48      .1       0
Bank Sta=141.6,158.1
XS Rating Curve= 0 ,0
Exp/Cntr=0.3,0.1

Type RM Length L Ch R = 1 ,5576    ,200.7,199.6,198.6
XS GIS Cut Line= 3
2247641.98526518555362.017728093 2247605.0854347 555459.35693609
2247564.36838037555780.639942876
#Sta/Elev= 30
       0 2747.59     3.9 2745.63    16.3 2737.01    27.7 2730.78    46.2 2718.15
    63.3 2708.86    84.5 2695.61   101.8 2681.72     114 2667.52   130.1 2654.96
   134.2  2653.4   138.2 2652.97   178.5 2653.77  202.15 2653.31   206.7 2652.75
   211.62653.312   222.9 2654.48   235.4 2653.11   255.1 2654.47   275.3 2653.81
   279.3 2654.69   295.4 2662.66   307.5 2671.54   311.6 2673.33   319.6  2674.6
   331.7 2674.72   335.8    2676   355.9 2693.76   360.6 2696.73     428 2731.74
#Mann= 5 ,-1,0
       0      .1       0  202.15    .045       0   211.6      .1       0
   274.1     .06       0   374.1      .1       0
Bank Sta=202.15,211.6
XS Rating Curve= 0 ,0
Exp/Cntr(USF)=0,0
Exp/Cntr=0.3,0.1

Type RM Length L Ch R = 1 ,5377    ,468.4,471.4,471.9
XS GIS Cut Line= 4
2247521.51860786555353.1198628372247412.86234138 555462.09886377
2247412.10216584555603.8849934692247441.94749553555750.937934947
#Sta/Elev= 30
       0 2732.03    11.4  2725.9    20.8 2719.58    39.6 2711.86   109.5 2674.93
   120.9 2671.44   132.2 2666.36   150.9  2655.6     161 2653.84   173.6 2649.69
     177 2648.43   188.72641.618     193 2640.55   201.12641.522     217 2644.33
     229 2648.87     241 2649.16     253 2653.32     273 2656.42     289    2661
   317.7  2662.4   333.7 2662.02   341.9 2667.39   362.3  2672.9   382.7 2682.73
   386.8 2684.88     399 2693.43   411.3 2698.31   423.5 2706.45   445.7 2719.35
#Mann= 5 ,-1,0
       0      .1       0   188.7    .045       0   201.1      .1       0
  315.68     .06       0  425.68      .1       0
Bank Sta=188.7,201.1
XS Rating Curve= 0 ,0
Exp/Cntr=0.3,0.1

Type RM Length L Ch R = 1 ,4905    ,523.5,522.7,520.6
XS GIS Cut Line= 4
  2247021.056589555277.9295579342246991.10910654555396.162678749
2246964.57435026555502.3874856192246936.90725873555663.939187029
#Sta/Elev= 30
       0    2716     3.4 2712.98    19.9 2704.78    32.2 2696.01    40.5 2691.55
      57 2681.37    68.8 2675.82   102.4 2657.68   114.8  2649.8   131.3 2637.93
   135.1  2636.2   139.5 2635.18   147.8 2630.15   152.62628.534   164.2 2627.78
   170.52628.604   176.6 2631.38   184.9 2632.95   205.5 2632.77     222 2633.43
   234.4 2636.26   254.6 2636.73   266.8 2645.29   282.7 2654.44   295.2 2656.12
   307.3 2663.24   338.2 2678.07   364.2 2694.31   380.4 2701.85   395.4 2711.39
#Mann= 5 ,-1,0
       0      .1       0   152.6    .045       0   170.5      .1       0
  261.46     .06       0  361.46      .1       0
Bank Sta=152.6,170.5
XS Rating Curve= 0 ,0
Exp/Cntr=0.3,0.1

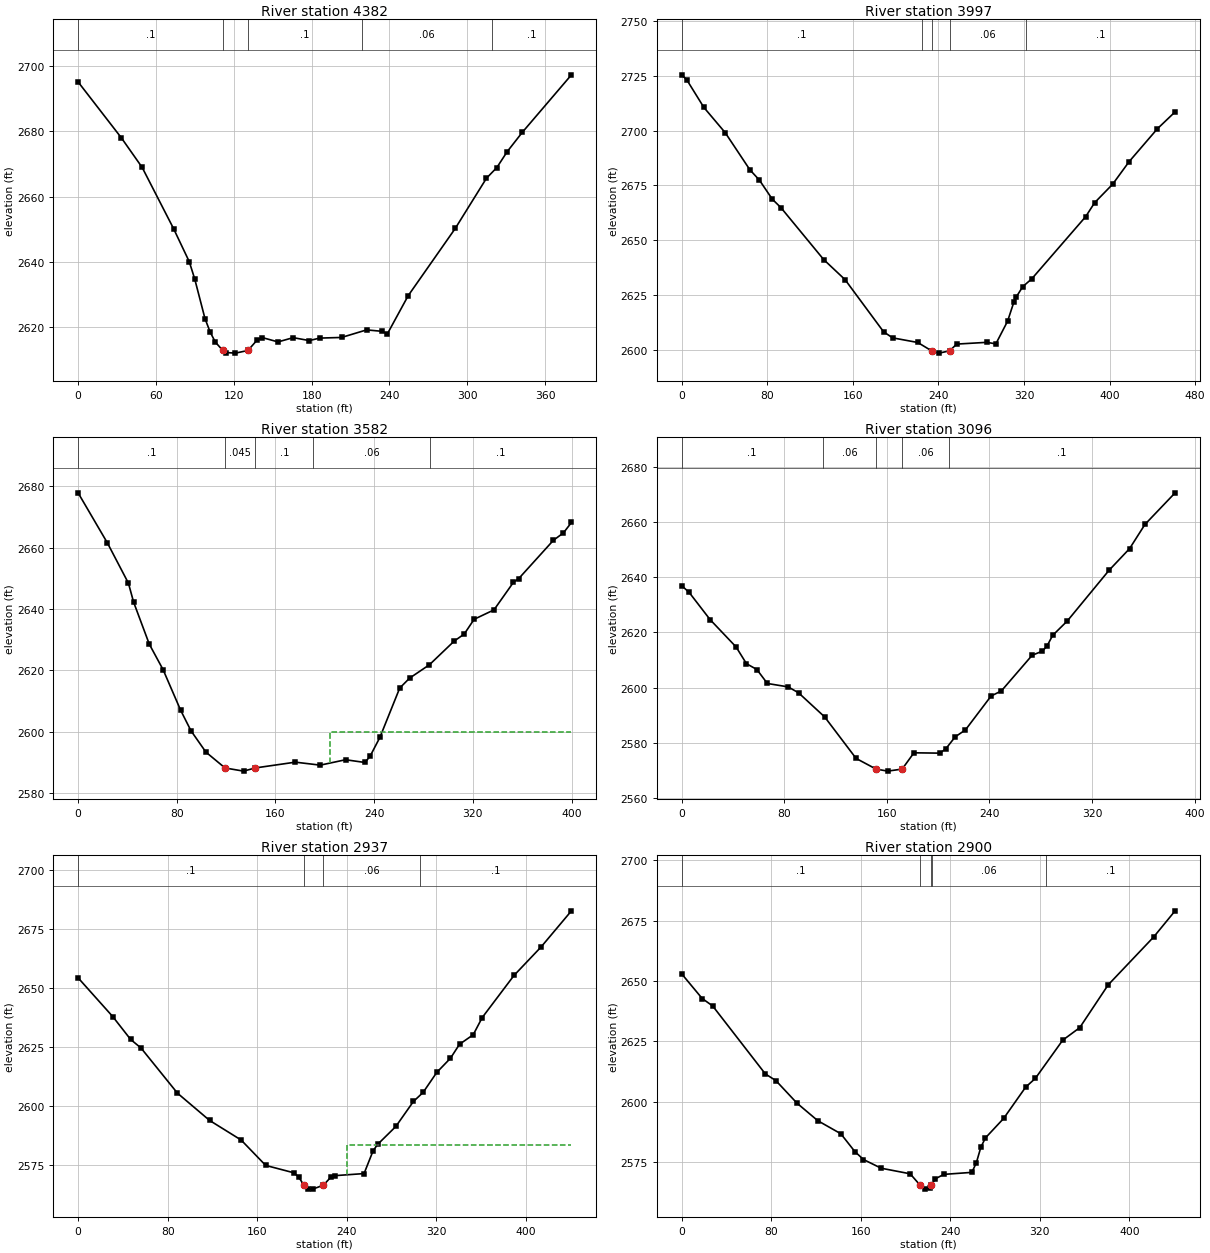
Type RM Length L Ch R = 1 ,4382    ,382.7,385.5,380
XS GIS Cut Line= 4
2246486.94880121555212.0774373552246473.90871477555321.528584701
2246466.23203115555400.0376695142246449.11563924 555590.47351546
#Sta/Elev= 30
       0 2695.19    33.3 2678.06    49.4 2668.94    73.6 2650.17    85.7 2640.03
    89.9 2634.73    97.8 2622.59   101.8 2618.44   105.8 2615.35   111.5 2612.82
   113.9 2612.15   121.3 2611.97  130.95 2612.79     138 2615.99     142 2616.74
   154.1 2615.41   165.8 2616.72   178.2 2615.82   186.2 2616.58   203.1 2616.78
   222.4  2619.1   234.4 2618.66   238.4 2617.88   254.5 2629.63   290.7 2650.21
   314.8 2665.64   322.8 2668.92   330.8 2673.81   342.5 2679.76   380.3 2697.36
#Mann= 5 ,-1,0
       0      .1       0   111.5    .045       0  130.95      .1       0
  219.11     .06       0  319.11      .1       0
Bank Sta=111.5,130.95
XS Rating Curve= 0 ,0
Exp/Cntr=0.3,0.1

Type RM Length L Ch R = 1 ,3997    ,412.8,415.1,414.5
XS GIS Cut Line= 4
2246115.85160631555208.5053748542246119.75119319 555402.90612514
2246119.75119319555480.2066591972246177.17079457555660.908481351
#Sta/Elev= 30
       0  2725.4     4.7 2723.14    20.7 2710.55    40.7 2699.01    63.7 2682.14
    72.7 2677.37    84.7 2668.71    92.7  2664.9   132.7 2641.22   152.7 2632.06
   188.7 2608.31   197.1 2605.53   220.7 2603.41  233.572599.624   240.7 2598.56
  250.552599.625   257.1 2602.68   285.4 2603.48   293.7 2602.77   304.7 2613.15
   310.5 2621.75   312.8 2624.18   318.9 2628.88   327.3 2632.43   377.7 2660.77
   386.1 2667.15   402.9 2675.54   418.4 2685.89   444.8 2700.85   461.3 2708.51
#Mann= 5 ,-1,0
       0      .1       0  224.44     .06       0  233.57    .045       0
  250.55     .06       0  321.74      .1       0
Bank Sta=233.57,250.55
XS Rating Curve= 0 ,0
Exp/Cntr=0.3,0.1

Type RM Length L Ch R = 1 ,3582    ,483.8,485.5,485.4
XS GIS Cut Line= 4
2245789.40262801555250.7045999042245759.50685328555336.339498308
2245741.23830362 555489.666507612245756.52112458  555643.6493553
#Sta/Elev= 30
       0 2677.84    23.8 2661.49    40.8 2648.41      45 2642.24    57.7 2628.56
    68.9 2620.23    83.1 2607.03    91.5 2600.33   103.6 2593.38  119.12 2588.21
   134.1 2587.18   143.62588.215   176.1  2590.1   196.3 2589.13   216.8 2590.89
   232.5    2590   236.6 2591.98   244.6 2598.14   260.7 2614.24   268.7 2617.47
   284.8 2621.84   304.9 2629.56     313 2631.84     321 2636.64   337.1 2639.71
   352.9  2648.7   357.2 2649.92   385.3 2662.39   393.4 2664.79   399.9 2668.18
#Mann= 5 ,-1,0
       0      .1       0  119.12    .045       0   143.6      .1       0
   190.7     .06       0  285.11      .1       0
#XS Ineff= 2 , 0
                          204.27         2599.89
Permanent Ineff=
       F       F
Bank Sta=119.12,143.6
XS Rating Curve= 0 ,0
Exp/Cntr=0.3,0.1

Type RM Length L Ch R = 1 ,3096    ,158.2,158.9,159.6
XS GIS Cut Line= 4
2245317.43733809555227.4745422622245297.07603628555341.012627575
2245280.96787263555412.2165070782245278.43971906555608.601412892
#Sta/Elev= 30
       0 2636.89     5.8 2634.46    22.1 2624.63    42.4 2614.72    50.5 2608.66
    58.6 2606.56    66.8  2601.5      83 2600.27    91.1 2598.13   111.5 2589.39
     136 2574.38   151.5 2570.54   160.6 2569.78  171.92 2570.52   181.1 2576.41
   201.3 2576.29   205.9 2577.82   213.3 2582.19   221.3 2584.71   241.3 2596.97
   249.3 2598.81   273.3 2611.71   281.3 2613.21   284.9 2615.05   289.3 2618.91
   300.7 2624.11   333.3 2642.47   349.3 2650.31   361.3 2659.07   384.8  2670.5
#Mann= 5 ,-1,0
       0      .1       0     110     .06       0   151.5    .045       0
  171.92     .06       0  208.35      .1       0
Bank Sta=151.5,171.92
XS Rating Curve= 0 ,0
Exp/Cntr=0.3,0.1

Type RM Length L Ch R = 1 ,2937    ,38.3,37.8,37.8
XS GIS Cut Line= 4
2245242.94926742555157.2786613912245141.04922231555321.787109938
 2245123.2857943555381.5126295342245091.08471374555563.680372078
#Sta/Elev= 30
       0  2654.4      31 2637.93    46.9 2628.27    56.3 2624.56    88.8 2605.43
   117.5 2593.86   145.7 2585.54   167.6 2574.77   192.8 2571.63   197.1 2569.84
  201.742566.378   205.4 2564.86   209.6  2564.7   219.22566.378   225.9 2569.83
   229.1 2570.41   255.5  2571.3   263.6 2581.01   267.7 2583.73   283.9  2591.3
   299.6 2601.91   308.3 2605.77   320.5 2614.27   332.7 2620.26   340.8  2626.2
     353 2630.22   361.1 2637.55   389.5 2655.43   413.6 2667.47   440.8 2682.84
#Mann= 4 ,-1,0
       0      .1       0  201.74    .045       0   219.2     .06       0
  305.82      .1       0
#XS Ineff= 2 , 0
                          240.67         2583.32
Permanent Ineff=
       F       F
Bank Sta=201.74,219.2
XS Rating Curve= 0 ,0
Exp/Cntr=0.3,0.1

Type RM Length L Ch R = 1 ,2900    ,194.4,196.7,198.6
XS GIS Cut Line= 4
2245208.20745436555141.6448455142245106.30740925555306.153294061
2245088.54398124555365.8788136572245056.34290069555548.046556201
#Sta/Elev= 30
       0 2652.95    18.3 2642.76    27.7 2639.65    74.7 2611.53    84.1 2608.77
     103 2599.41   121.6 2592.14   142.1 2586.76   154.7 2579.36   162.4 2576.07
   178.2 2572.47   204.1 2570.16  212.962565.447   217.5 2563.81   221.7  2564.4
  223.14 2565.45   226.6 2568.09   234.2 2569.92   259.2 2570.75   263.2 2574.69
   267.3 2581.24   271.4 2585.05   287.6 2593.08   307.3 2606.06     316 2609.71
   340.4 2625.51   355.6 2630.69     381 2648.41   421.7 2668.27   440.8 2679.08
#Mann= 5 ,-1,0
       0      .1       0  212.96    .045       0  223.14      .1       0
  223.51     .06       0  325.82      .1       0
Bank Sta=212.96,223.14
XS Rating Curve= 0 ,0
Exp/Cntr=0.3,0.1

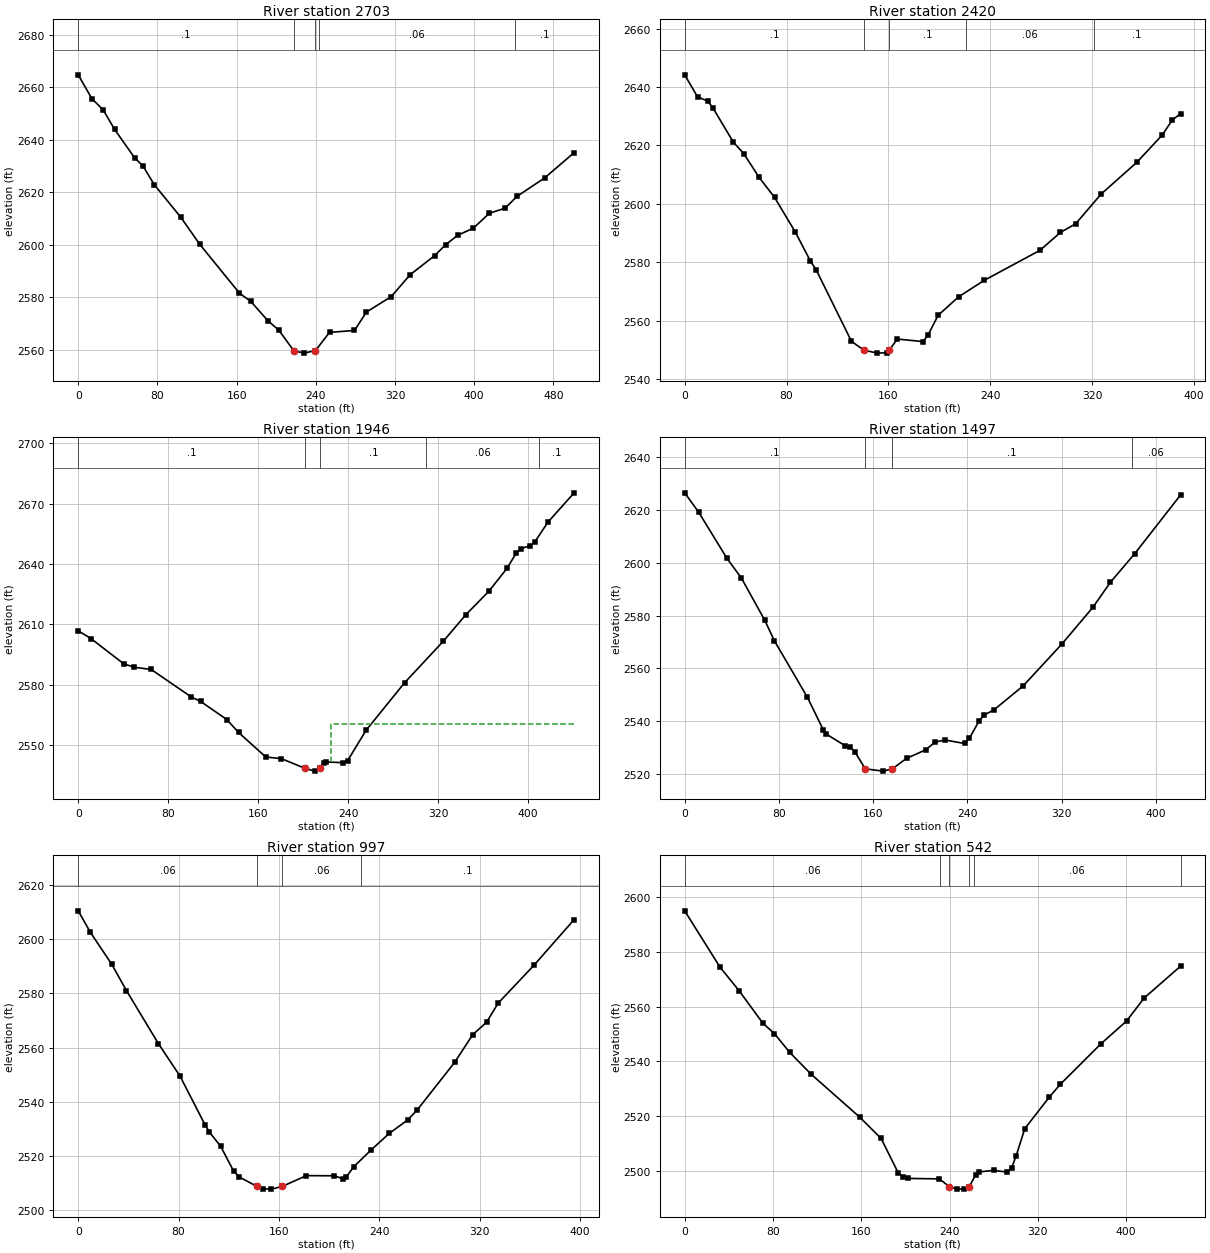
Type RM Length L Ch R = 1 ,2703    ,289.7,282.4,276.7
XS GIS Cut Line= 4
2245097.01342365555063.5649585162244951.24533492555205.168244713
2244916.26099363  555250.98107262244927.92244072555490.873698627
#Sta/Elev= 30
       0 2664.69    13.8 2655.62    25.3 2651.28    36.8 2643.86    56.9 2633.11
    65.5 2629.89    76.9 2622.79   103.6 2610.42   122.9 2600.04   162.9 2581.47
   174.3 2578.34   191.8  2570.9   202.6 2567.39  217.72 2559.59   228.1 2558.62
   239.7 2559.61   253.9 2566.54   279.1 2567.25   291.1 2574.26   316.3 2580.19
   335.4 2588.53   360.1 2595.79   371.2 2599.95   383.2  2603.5   399.2 2606.25
   415.2 2611.89   431.3 2613.88   443.3 2618.38   471.3 2625.43     501 2635.04
#Mann= 5 ,-1,0
       0      .1       0  217.72    .045       0   239.7      .1       0
  243.22     .06       0  440.87      .1       0
Bank Sta=217.72,239.7
XS Rating Curve= 0 ,0
Exp/Cntr(USF)=0,0
Exp/Cntr=0.3,0.1

Type RM Length L Ch R = 1 ,2420    ,472.6,474.5,476.3
XS GIS Cut Line= 4
2244681.39067645 555011.15715206 2244665.6741072555138.432322945
2244662.31130625555211.2930102652244659.54655448555399.592363408
#Sta/Elev= 30
       0 2644.18    10.1 2636.65    18.2 2635.17    22.2 2632.83    38.3  2621.1
    46.4 2617.22    58.5 2609.06    70.6 2602.23    86.7 2590.52    98.8 2580.42
   103.4 2577.35     131 2552.98  140.75 2549.96   151.4 2548.95     159 2549.07
   160.8    2550     167 2553.77   187.1  2552.9   191.1 2555.12   199.1 2561.92
   215.1  2568.2   235.1 2573.81   279.1 2584.14   295.1 2590.25   307.1 2593.22
   327.1 2603.39   355.1 2614.23   375.1 2623.61   383.1 2628.79   389.5 2630.89
#Mann= 5 ,-1,0
       0      .1       0  140.75    .045       0   160.8      .1       0
  221.18     .06       0  321.18      .1       0
Bank Sta=140.75,160.8
XS Rating Curve= 0 ,0
Exp/Cntr=0.3,0.1

Type RM Length L Ch R = 1 ,1946    ,452.2,448.7,445.3
XS GIS Cut Line= 4
2244261.35487844554938.3751802722244208.05358188555092.698268748
2244184.06454983555165.1468044822244152.63585078555363.992853777
#Sta/Elev= 30
       0 2606.75    11.4 2602.87    40.4 2590.34    49.5 2588.64    64.9 2587.51
   100.6  2573.8   108.8 2571.62   132.1  2562.6   142.6 2556.15   166.7 2543.96
   180.6 2543.14  201.19 2538.41   210.1 2536.92  215.012538.406   218.6 2541.02
   220.5 2541.48   235.4 2541.12   239.6  2542.2   255.8 2557.14   290.1 2580.88
   324.7 2601.64   344.4 2614.63   365.2 2626.52   381.4 2637.99   389.5  2645.5
   393.5 2647.66   401.6 2649.01   405.7 2650.82   417.7  2660.9   440.9 2675.42
#Mann= 5 ,-1,0
       0      .1       0  201.19    .045       0  215.01      .1       0
  309.59     .06       0  409.59      .1       0
#XS Ineff= 2 , 0
                          224.59         2560.59
Permanent Ineff=
       F       F
Bank Sta=201.19,215.01
XS Rating Curve= 0 ,0
Exp/Cntr=0.3,0.1

Type RM Length L Ch R = 1 ,1497    ,513.7,499.9,492
XS GIS Cut Line= 4
2243753.27267648554857.3644731752243764.71632255554998.811376468
2243766.18721169 555056.176052812243820.98507549555270.934867186
#Sta/Elev= 30
       0 2626.39    11.9 2619.06    35.9 2601.59      48 2594.26      68 2578.18
    76.1 2570.47   104.2 2549.03   117.6  2536.8   120.2 2535.15   136.3 2530.72
   140.3  2530.3   144.3 2528.54  153.262522.024   168.3 2521.15  176.342522.023
   188.3 2525.98   204.5 2529.19   212.7 2532.17     221 2532.92   237.5  2531.6
   241.6 2533.57   249.9 2540.15     254 2542.36   262.3 2544.24   287.3 2553.39
   320.2 2569.25   346.5 2583.12   361.3 2592.56     382 2603.41   420.9 2625.61
#Mann= 4 ,-1,0
       0      .1       0  153.26    .045       0  176.34      .1       0
  379.29     .06       0
Bank Sta=153.26,176.34
XS Rating Curve= 0 ,0
Exp/Cntr=0.3,0.1

Type RM Length L Ch R = 1 ,997     ,454.2,455.9,457.9
XS GIS Cut Line= 4
2243273.44109048555238.4059641372243376.93919221555316.115655866
2243440.92286966555356.5651071322243597.77912387555463.868646823
#Sta/Elev= 30
       0 2610.45     9.6 2602.58    26.8 2590.67    38.4 2581.04    63.9 2561.45
    81.1 2549.47   101.1 2531.45   104.5 2528.81   113.5 2523.58   123.9 2514.35
   128.5  2512.2  142.522508.732   147.4  2507.9   153.9 2507.75  162.532508.733
   181.8 2512.73   204.2 2512.67   210.8 2511.57   213.7 2512.27   219.4 2515.93
   233.3 2522.15   247.8  2528.3   262.4 2533.22     270 2536.89     300 2554.55
   314.4 2564.76   325.4 2569.34   334.5  2576.3   363.3 2590.43   395.2 2607.24
#Mann= 4 ,-1,0
       0     .06       0  142.52    .045       0  162.53     .06       0
  225.12      .1       0
Bank Sta=142.52,162.53
XS Rating Curve= 0 ,0
Exp/Cntr=0.3,0.1

Type RM Length L Ch R = 1 ,542     ,291,289.2,285.7
XS GIS Cut Line= 4
2242973.94781592555570.8045821472243139.63824385555685.900110927
2243202.15103217555748.4128992482243361.06270215555758.705401975
#Sta/Elev= 30
       0 2595.01      32 2574.45    49.3 2565.84    70.9 2553.93    81.3 2550.19
    95.2 2543.29   114.7  2535.3   158.6 2519.66     178 2511.87   193.5 2499.33
   197.5 2497.96   202.5 2497.28   230.8 2497.11  239.722494.305   246.9 2493.37
   253.4 2493.46     2582494.305   263.8 2498.71   266.7 2499.65   279.9 2500.21
   292.2 2499.61   296.2 2501.06   300.2 2505.33   308.2 2515.46   330.4 2526.97
   340.3 2531.62   377.2 2546.45   400.4 2554.76   416.4 2563.19   449.4 2574.81
#Mann= 6 ,-1,0
       0     .06       0  231.74      .1       0  239.72    .045       0
     258      .1       0  261.74     .06       0  449.39      .1       0
Bank Sta=239.72,258
XS Rating Curve= 0 ,0
Exp/Cntr=0.3,0.1

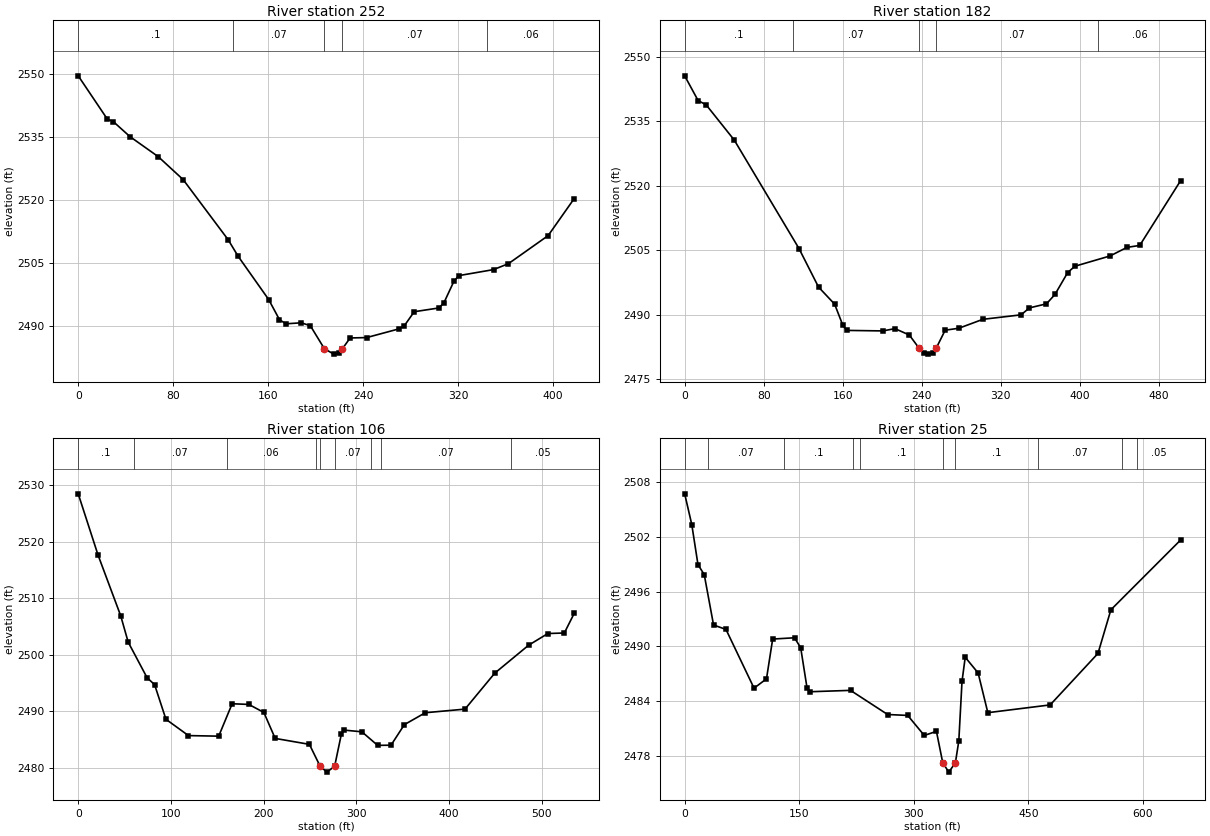
Type RM Length L Ch R = 1 ,252     ,72.2,70.7,69.2
XS GIS Cut Line= 4
2242941.05841144555797.1974239722242988.42221179555941.110509655
 2243095.9016049556000.6188741982243233.13518027555959.327355943
#Sta/Elev= 30
       0 2549.57    24.6 2539.23    29.5 2538.68    43.6 2535.09    67.4 2530.32
    88.4 2524.85   126.3 2510.53   134.7 2506.59   160.4  2496.3   169.5  2491.5
   174.9 2490.51   187.8 2490.75   195.5 2490.06   207.3 2484.59   215.2 2483.29
   219.8 2483.49  222.49 2484.56     229 2487.14   242.9 2487.23   270.1  2489.3
   274.6 2490.03     283 2493.39   303.9 2494.29   308.1 2495.57   316.4 2500.62
   320.6 2501.99   349.8 2503.42   362.4 2504.84   395.8 2511.52   417.7 2520.32
#Mann= 5 ,-1,0
       0      .1       0     130     .07       0   207.3    .045       0
  222.49     .07       0  344.36     .06       0
Bank Sta=207.3,222.49
XS Rating Curve= 0 ,0
Exp/Cntr(USF)=0,0
Exp/Cntr=0.3,0.1

Type RM Length L Ch R = 1 ,182     ,76,76.1,76
XS GIS Cut Line= 4
2242931.00464979555811.7604400922242968.37139845556017.367660447
2243053.09461274556047.1531654712243242.69609345 555973.02149978
#Sta/Elev= 30
       0 2545.54    13.6 2539.79    21.8 2538.78    50.2  2530.6   115.8 2505.36
   135.6 2496.39   151.9 2492.42     160 2487.63   164.1 2486.31   200.7 2486.19
     213 2486.72   227.5 2485.25  237.622482.127   242.7 2480.96   246.9 2480.79
   251.2 2481.07  254.692482.126   263.9 2486.36   277.7 2486.81   302.1 2488.89
   340.7 2489.93   349.3 2491.55   366.5 2492.49   375.1 2494.67     388 2499.77
   395.3 2501.24   430.9 2503.63   448.1 2505.63     461 2506.08   502.4 2521.15
#Mann= 5 ,-1,0
       0      .1       0     110     .07       0  237.62    .045       0
  254.69     .07       0  418.78     .06       0
Bank Sta=237.62,254.69
XS Rating Curve= 0 ,0
Exp/Cntr(USF)=0,0
Exp/Cntr=0.3,0.1

Type RM Length L Ch R = 1 ,106     ,81.3,81,80.6
XS GIS Cut Line= 4
2242897.15907589555864.1041321442242937.17342499556086.920755402
2243021.89663928556116.7062604262243226.05992245556038.603194065
#Sta/Elev= 30
       0 2528.52    21.4 2517.67    45.8 2506.93    53.9 2502.25    74.2 2495.97
    82.4 2494.71    94.6 2488.59   118.9  2485.7   151.5  2485.6     166 2491.34
     184 2491.22   200.2  2489.8   212.4  2485.2   249.3 2484.15  260.862480.274
   268.2 2479.23  276.522480.273   283.8 2485.99     287 2486.67   305.9 2486.37
   322.9 2483.97   337.3    2484   351.7 2487.64   374.3 2489.75   417.1 2490.39
   449.2 2496.76   485.7 2501.71   506.5 2503.78   524.2 2503.87   534.8 2507.33
#Mann= 9 ,-1,0
       0      .1       0      60     .07       0     160     .06       0
  256.38     .07       0  260.86    .045       0  276.52     .07       0
  316.19      .1       0  326.19     .07       0  466.19     .05       0
Bank Sta=260.86,276.52
XS Rating Curve= 0 ,0
Exp/Cntr(USF)=0,0
Exp/Cntr=0.3,0.1

Type RM Length L Ch R = 1 ,25      ,15.4,15.4,15.4
XS GIS Cut Line= 4
2242821.12051017555896.0982230462242871.47754419556153.171581227
 2242976.7047698556185.4737130412243238.32424342556093.535409487
#Sta/Elev= 30
       0 2506.68     9.3 2503.32    17.4 2498.94    25.6 2497.85    37.8 2492.34
    54.1 2491.85    90.8 2485.43   107.1 2486.45   115.2  2490.8   143.8 2490.94
   151.9 2489.85   160.1  2485.5   164.1 2485.04   217.1 2485.19   265.7 2482.55
     292 2482.45   313.7 2480.26   329.6 2480.71  337.872477.276   345.8 2476.25
  354.432477.276   358.9 2479.66   363.1 2486.18   367.3 2488.81   384.2 2487.09
   396.9 2482.75   478.5  2483.6   541.1 2489.23     558    2494   649.3 2501.63
#Mann= 10 ,-1,0
       0      .1       0      30     .07       0     130      .1       0
     220     .06       0     230      .1       0  337.87    .045       0
  354.43      .1       0  462.03     .07       0  572.03      .1       0
  592.03     .05       0
Bank Sta=337.87,354.43
XS Rating Curve= 0 ,0
Exp/Cntr(USF)=0,0
Exp/Cntr=0.3,0.1
LCMann Table=0

Chan Stop Cuts=-1
Use User Specified Reach Order=0
Composite Channel Slope=5